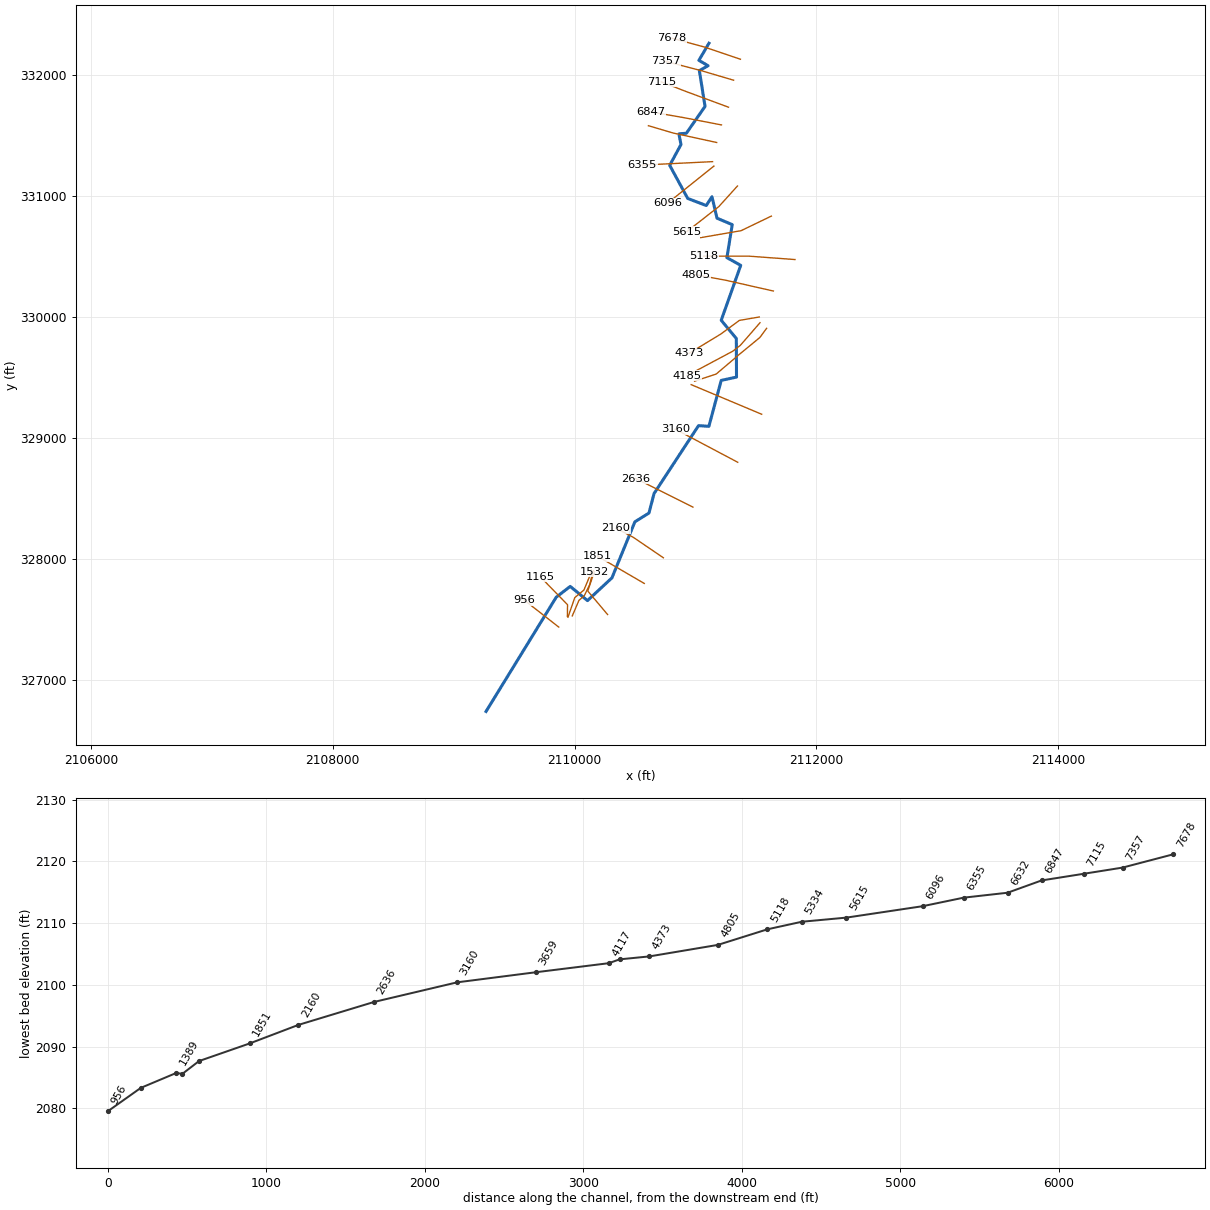
--- MLGNCKTR5.prj (project) ---

Proj Title=MLGNCKTR5
Current Plan=p01
Default Exp/Contr=0.3,0.1
English Units
Geom File=g01
Flow File=f01
Plan File=p01
Y Axis Title=Elevation
X Axis Title(PF)=Main Channel Distance
X Axis Title(XS)=Station
BEGIN DESCRIPTION:
Stream Name- Milligan Creek Tributary 5
Flood Zone: Zone A
Greenbrier County, WV
County-Wide Study
WVDHSEM-2018-3, Flood Risk Project
HEC-RAS Version: 5.0.7
General Notes:
For the Hydrology XXXXX (the HEC-HMS version 4.2.1 or Regression, regression with gage weighting, etc.) was used.
END DESCRIPTION:
DSS Export Rating Curves= 0
DSS Export Rating Curve Sorted= 0
DSS Export Volume Flow Curves= 0
DXF Filename=MLGNCKTR5.G2.
DXF OffsetX= 0
DXF OffsetY= 0
DXF ScaleX= 1
DXF ScaleY= 10

--- MLGNCKTR5.p01 (plan) ---

Plan Title=Floodplain
Program Version=5.07
Short Identifier=Floodplain
Geom File=g01
Flow File=f01
Subcritical Flow
K Sum by GR= 0
Std Step Tol= 0.01
Critical Tol= 0.01
Num of Std Step Trials= 20
Max Error Tol= 0.3
Flow Tol Ratio= 0.001
Split Flow NTrial= 30
Split Flow Tol= 0.02
Split Flow Ratio= 0.02
Log Output Level= 0
Friction Slope Method= 1
Unsteady Friction Slope Method= 2
Unsteady Bridges Friction Slope Method= 1
Parabolic Critical Depth
Global Vel Dist= 0 , 0 , 0
Global Log Level= 0
CheckData=True
Encroach Param=-1 ,0,0, 0
Computation Interval=1MIN
Output Interval=1HOUR
Instantaneous Interval=1HOUR
Mapping Interval=1HOUR
Computation Time Step Use Courant=        0
Computation Time Step Use Time Series=    0
Computation Time Step Count To Double=0
Computation Time Step Max Doubling=0
Computation Time Step Max Halving=0
Computation Time Step Residence Courant=0
Run HTab= 0
Run UNet= 0
Run Sediment= 0
Run PostProcess= 0
Run WQNet= 0
Run RASMapper= 0
UNET Theta= 1
UNET Theta Warmup= 1
UNET ZTol= 0.02
UNET ZSATol= 0.02
UNET MxIter= 20
UNET Max Iter WO Improvement= 0
UNET MaxInSteps= 0
UNET DtIC= 0
UNET DtMin= 0
UNET MaxCRTS= 20
UNET WFStab= 2
UNET SFStab= 1
UNET WFX= 1
UNET SFX= 1
UNET 1D Methodology=Finite Difference
UNET DSS MLevel= 4
UNET Pardiso=0
UNET DZMax Abort= 100
UNET Use Existing IB Tables=-1
UNET Froude Reduction=False
UNET Froude Limit= 0.8
UNET Froude Power= 4
UNET D1 Cores= 0
UNET D2 Coriolis=0
UNET D2 Cores= 0
UNET D2 Theta= 1
UNET D2 Theta Warmup= 1
UNET D2 Z Tol= 0.01
UNET D2 Volume Tol= 0.01
UNET D2 Max Iterations= 20
UNET D2 Equation= 0
UNET D2 RampUpFraction=0.1
UNET D2 TimeSlices= 1
UNET D2 BCVolumeCheck=0
UNET D1D2 MaxIter= 0
UNET D1D2 ZTol=0.01
UNET D1D2 QTol=0.1
UNET D1D2 MinQTol=1
Write IC File= 0
Write IC File at Fixed DateTime=0
Write IC File at Sim End=0
Echo Input=False
Echo Parameters=False
Echo Output=False
Write Detailed= 0
HDF Write Warmup=0
HDF Write Time Slices=0
HDF Flush=0
HDF Face Node Velocities=0
HDF Compression= 1
HDF Chunk Size= 1
HDF Spatial Parts= 1
HDF Use Max Rows=0
HDF Fixed Rows= 1
Calibration Method= 0
Calibration Iterations= 20
Calibration Max Change=0.05
Calibration Tolerance=0.2
Calibration Maximum=1.5
Calibration Minimum=0.5
Calibration Optimization Method= 1
WQ AD Non Conservative
WQ ULTIMATE=-1
WQ Max Comp Step=1HOUR
WQ Output Interval=15MIN
WQ Output Selected Increments= 0
WQ Output face flow=0
WQ Output face velocity=0
WQ Output face area=0
WQ Output face dispersion=0
WQ Output cell volume=0
WQ Output cell surface area=0
WQ Output cell continuity=0
WQ Output cumulative cell continuity=0
WQ Output face conc=0
WQ Output face dconc_dx=0
WQ Output face courant=0
WQ Output face peclet=0
WQ Output face adv mass=0
WQ Output face disp mass=0
WQ Output cell mass=0
WQ Output cell source sink temp=0
WQ Output nsm pathways=0
WQ Output nsm derived pathways=0
WQ Output MaxMinRange=-1
WQ Daily Max Min Mean=-1
WQ Daily Range=0
WQ Daily Time=0
WQ Create Restart=0
WQ Fixed Restart=0
WQ System Summary=0
WQ Write To DSS=0
WQ Use Fixed Temperature=0
Sorting and Armoring Iterations= 10
XS Update Threshold= 0.02
Bed Roughness Predictor= 0
Hydraulics Update Threshold= 0.02
Energy Slope Method= 1
Volume Change Method= 1
Sediment Retention Method= 0
XS Weighting Method= 0
Number of US Weighted Cross Sections= 1
Number of DS Weighted Cross Sections= 1
Upstream XS Weight=0
Main XS Weight=1
Downstream XS Weight=0
Number of DS XS's Weighted with US Boundary= 1
Upstream Boundary Weight= 1
Weight of XSs Associated with US Boundary= 0
Number of US XS's Weighted with DS Boundary= 1
Downstream Boundary Weight= 0.5
Weight of XSs Associated with DS Boundary= 0.5
Percentile Method= 0
Sediment Output Level= 3
Mass or Volume Output= 0
Output Increment Type= 1
Profile and TS Output Increment= 1
XS Output Flag= 0
XS Output Increment= 10
Write Gradation File= 0
Read Gradation Hotstart= 0
Write HDF5 File= 1
Write Binary Output= 1
Write DSS Sediment File= 0
SV Curve= 0
Specific Gage Flag= 0

--- MLGNCKTR5.f01 (steady flow) ---

Flow Title=Flow
Program Version=5.07
Number of Profiles= 6
Profile Names=f1p,f10p,f4p,f2p,f02p,f1pplus
River Rch & RM=BURNSRN,Main            ,9203
     572     302     402     484     799     846
River Rch & RM=BURNSRN,Main            ,7195
     649     345     457     550     905     960
River Rch & RM=BURNSRN,Main            ,4526
    1220     661     867    1040    1670    1800
River Rch & RM=BURNSRNT1,Main            ,2875
     504     265     353     426     705     745
River Rch & RM=BURNSRNT1,Main            ,2198
     669     356     472     568     932     990
River Rch & RM=CLBRSNCKT1,Main            ,2948
     116    57.4    78.7    96.5     166     171
River Rch & RM=CLBRSNCKT1,Main            ,2280
     138    69.1    94.4     116     198     210
River Rch & RM=CLBRSNCKT1,Main            ,1216
     156    78.2     107     130     223     230
River Rch & RM=CLBRSNCKT1,Main            ,243
     178    89.6     122     149     253     300
River Rch & RM=CLBRSNCKT2,Main            ,5369
     223     114     154     187     317     330
River Rch & RM=CLBRSNCKT2,Main            ,3799
     483     253     338     408     676     714
River Rch & RM=INDIANCK,Main            ,11519
     313     162     218     264     443     463
River Rch & RM=INDIANCK,Main            ,9807
     520     274     365     440     728     769
River Rch & RM=INDIANCK,Main            ,8108
     581     307     409     492     812     860
River Rch & RM=INDIANCK,Main            ,6227
     647     344     456     549     902     958
River Rch & RM=LTROARCK,Main            ,4000
     648     344     456     549     903     958
River Rch & RM=MLGNCKTR5,Main            ,7678
     581     307     409     492     812     860
River Rch & RM=MLGNCKTR5,Main            ,5118
     654     347     461     554     911     967
River Rch & RM=MLGNCKTR5,Main            ,2636
     728     388     514     617    1010    1080
River Rch & RM=ROARINGCK,Main            ,17918
     544     287     382     461     761     805
River Rch & RM=ROARINGCK,Main            ,16996
     613     325     431     519     855     906
River Rch & RM=ROARINGCK,Main            ,14906
     713     380     504     605     992    1060
River Rch & RM=ROARINGCK,Main            ,11661
     864     464     612     734    1200    1280
River Rch & RM=ROARINGCK,Main            ,8657
     964     520     685     820    1330    1430
River Rch & RM=ROARINGCK,Main            ,4987
    1570     861    1120    1340    2150    2320
Boundary for River Rch & Prof#=BURNSRN,Main            , 1
Up Type= 0
Dn Type= 3
Dn Slope=0.0012
Boundary for River Rch & Prof#=BURNSRN,Main            , 2
Up Type= 0
Dn Type= 3
Dn Slope=0.0012
Boundary for River Rch & Prof#=BURNSRN,Main            , 3
Up Type= 0
Dn Type= 3
Dn Slope=0.0012
Boundary for River Rch & Prof#=BURNSRN,Main            , 4
Up Type= 0
Dn Type= 3
Dn Slope=0.0012
Boundary for River Rch & Prof#=BURNSRN,Main            , 5
Up Type= 0
Dn Type= 3
Dn Slope=0.0012
Boundary for River Rch & Prof#=BURNSRN,Main            , 6
Up Type= 0
Dn Type= 3
Dn Slope=0.0012
Boundary for River Rch & Prof#=BURNSRNT1,Main            , 1
Up Type= 0
Dn Type= 3
Dn Slope=0.00496
Boundary for River Rch & Prof#=BURNSRNT1,Main            , 2
Up Type= 0
Dn Type= 3
Dn Slope=0.00496
Boundary for River Rch & Prof#=BURNSRNT1,Main            , 3
Up Type= 0
Dn Type= 3
Dn Slope=0.00496
Boundary for River Rch & Prof#=BURNSRNT1,Main            , 4
Up Type= 0
Dn Type= 3
Dn Slope=0.00496
Boundary for River Rch & Prof#=BURNSRNT1,Main            , 5
Up Type= 0
Dn Type= 3
Dn Slope=0.00496
Boundary for River Rch & Prof#=BURNSRNT1,Main            , 6
Up Type= 0
Dn Type= 3
Dn Slope=0.00496
Boundary for River Rch & Prof#=CLBRSNCKT1,Main            , 1
Up Type= 0
Dn Type= 3
Dn Slope=0.00848
Boundary for River Rch & Prof#=CLBRSNCKT1,Main            , 2
Up Type= 0
Dn Type= 3
Dn Slope=0.00848
Boundary for River Rch & Prof#=CLBRSNCKT1,Main            , 3
Up Type= 0
Dn Type= 3
Dn Slope=0.00848
Boundary for River Rch & Prof#=CLBRSNCKT1,Main            , 4
Up Type= 0
Dn Type= 3
Dn Slope=0.00848
Boundary for River Rch & Prof#=CLBRSNCKT1,Main            , 5
Up Type= 0
Dn Type= 3
Dn Slope=0.00848
Boundary for River Rch & Prof#=CLBRSNCKT1,Main            , 6
Up Type= 0
Dn Type= 3
Dn Slope=0.00848
Boundary for River Rch & Prof#=CLBRSNCKT2,Main            , 1
Up Type= 0
Dn Type= 3
Dn Slope=0.00274
Boundary for River Rch & Prof#=CLBRSNCKT2,Main            , 2
Up Type= 0
Dn Type= 3
Dn Slope=0.00274
Boundary for River Rch & Prof#=CLBRSNCKT2,Main            , 3
Up Type= 0
Dn Type= 3
Dn Slope=0.00274
Boundary for River Rch & Prof#=CLBRSNCKT2,Main            , 4
Up Type= 0
Dn Type= 3
Dn Slope=0.00274
Boundary for River Rch & Prof#=CLBRSNCKT2,Main            , 5
Up Type= 0
Dn Type= 3
Dn Slope=0.00274
Boundary for River Rch & Prof#=CLBRSNCKT2,Main            , 6
Up Type= 0
Dn Type= 3
Dn Slope=0.00274
Boundary for River Rch & Prof#=INDIANCK,Main            , 1
Up Type= 0
Dn Type= 3
Dn Slope=0.00176
Boundary for River Rch & Prof#=INDIANCK,Main            , 2
Up Type= 0
Dn Type= 3
Dn Slope=0.00176
Boundary for River Rch & Prof#=INDIANCK,Main            , 3
Up Type= 0
Dn Type= 3
Dn Slope=0.00176
Boundary for River Rch & Prof#=INDIANCK,Main            , 4
Up Type= 0
Dn Type= 3
Dn Slope=0.00176
Boundary for River Rch & Prof#=INDIANCK,Main            , 5
Up Type= 0
Dn Type= 3
Dn Slope=0.00176
Boundary for River Rch & Prof#=INDIANCK,Main            , 6
Up Type= 0
Dn Type= 3
Dn Slope=0.00176
Boundary for River Rch & Prof#=LTROARCK,Main            , 1
Up Type= 0
Dn Type= 3
Dn Slope=0.04436
Boundary for River Rch & Prof#=LTROARCK,Main            , 2
Up Type= 0
Dn Type= 3
Dn Slope=0.04436
Boundary for River Rch & Prof#=LTROARCK,Main            , 3
Up Type= 0
Dn Type= 3
Dn Slope=0.04436
Boundary for River Rch & Prof#=LTROARCK,Main            , 4
Up Type= 0
Dn Type= 3
Dn Slope=0.04436
Boundary for River Rch & Prof#=LTROARCK,Main            , 5
Up Type= 0
Dn Type= 3
Dn Slope=0.04436
Boundary for River Rch & Prof#=LTROARCK,Main            , 6
Up Type= 0
Dn Type= 3
Dn Slope=0.04436
Boundary for River Rch & Prof#=MLGNCKTR5,Main            , 1
Up Type= 0
Dn Type= 3
Dn Slope=0.0247
Boundary for River Rch & Prof#=MLGNCKTR5,Main            , 2
Up Type= 0
Dn Type= 3
Dn Slope=0.0247
Boundary for River Rch & Prof#=MLGNCKTR5,Main            , 3
Up Type= 0
Dn Type= 3
Dn Slope=0.0247
Boundary for River Rch & Prof#=MLGNCKTR5,Main            , 4
Up Type= 0
Dn Type= 3
Dn Slope=0.0247
Boundary for River Rch & Prof#=MLGNCKTR5,Main            , 5
Up Type= 0
Dn Type= 3
Dn Slope=0.0247
Boundary for River Rch & Prof#=MLGNCKTR5,Main            , 6
Up Type= 0
Dn Type= 3
Dn Slope=0.0247
Boundary for River Rch & Prof#=ROARINGCK,Main            , 1
Up Type= 0
Dn Type= 3
Dn Slope=0.01435
Boundary for River Rch & Prof#=ROARINGCK,Main            , 2
Up Type= 0
Dn Type= 3
Dn Slope=0.01435
Boundary for River Rch & Prof#=ROARINGCK,Main            , 3
Up Type= 0
Dn Type= 3
Dn Slope=0.01435
Boundary for River Rch & Prof#=ROARINGCK,Main            , 4
Up Type= 0
Dn Type= 3
Dn Slope=0.01435
Boundary for River Rch & Prof#=ROARINGCK,Main            , 5
Up Type= 0
Dn Type= 3
Dn Slope=0.01435
Boundary for River Rch & Prof#=ROARINGCK,Main            , 6
Up Type= 0
Dn Type= 3
Dn Slope=0.01435
DSS Import GetInterval= 0
DSS Import GetPeak= 0
DSS Import FillOption= 0

--- MLGNCKTR5.g01 (geometry) ---

Geom Title=Geometry
Program Version=5.07

River Reach=MLGNCKTR5       ,Main
Reach XY= 30
2111112.00548381332264.3292607812111028.87704113332122.873178869
 2111104.9188838332078.4287139482111032.69658729332038.150907367
2111079.57149354331741.9703973682110925.40480712331520.442625195
2110863.25204429331514.8871901182110880.61323005 331427.03992486
2110787.31190747331254.6439442042110936.33949655330981.090685532
2111089.67285129 330922.479582282111136.89519778 330994.97976537
2111178.83966771330817.4797922822111304.67274937330764.702010691
2111260.50617105330491.3685678692111374.95049596330427.757474616
2111213.56171113329973.5907320382111338.56178921329822.757372275
2111339.95056596329503.5906877822111213.56171113329476.368629366
2111111.61736122329096.6462917032111025.78387147329102.202054858
 2110658.0060637328541.090972364 2110615.7840353328379.424300954
2110499.39516047328307.2020044482110309.39521238327843.313168451
2110107.17284778327655.2574421912109964.39524621327772.757535279
2109848.56181645327683.5907188652109267.86645556326738.681519449

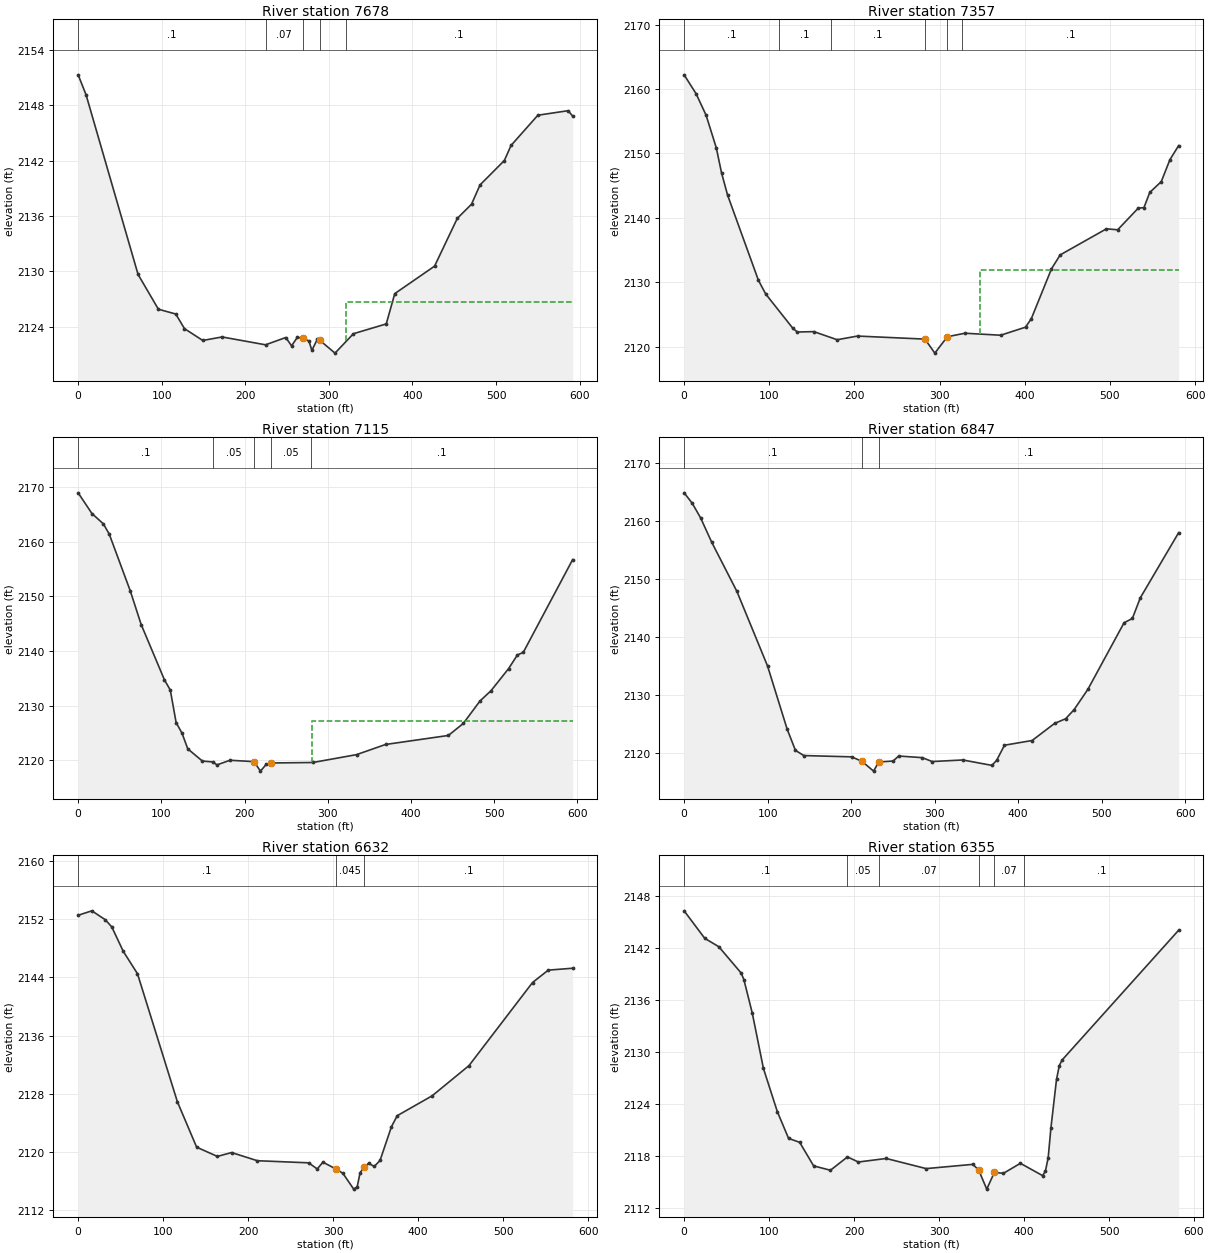
Type RM Length L Ch R = 1 ,7678    ,309.5,321,295.7
XS GIS Cut Line= 3
2111372.37241712332132.1438296142111075.15024254332232.838182032
2110807.09467629332305.754702866
#Sta/Elev= 30
       0 2151.27     9.4 2149.13    71.7 2129.67      96 2125.91   116.8 2125.39
   127.2 2123.81   149.1 2122.53   172.2 2122.91   224.2 2122.06   248.4 2122.85
   255.3 2121.95   262.3 2122.87  268.71 2122.78   276.1 2122.47   279.6 2121.46
   286.3 2122.68  288.93 2122.56   307.3 2121.16   329.3 2123.26   368.6 2124.32
   378.8  2127.6   426.4 2130.57   453.6 2135.74   470.6 2137.27   480.8 2139.36
   509.9    2142   517.9 2143.63     550  2146.9   586.2 2147.39   591.6 2146.81
#Mann= 5 ,-1 , 0
       0      .1       0   224.2     .07       0  268.71    .045       0
  288.93     .07       0  320.13      .1       0
#XS Ineff= 2 , 0
                          320.88         2126.73
Permanent Ineff=
       F       F
Bank Sta=268.71,288.93
XS Rating Curve= 0 ,0
Exp/Cntr=0.3,0.1

Type RM Length L Ch R = 1 ,7357    ,240.4,242.1,240.8
XS GIS Cut Line= 3
2111316.00671622331958.7639270282111050.93145895332036.889098868
2110756.48683786332113.972278029
#Sta/Elev= 30
       0 2162.21      14 2159.29    25.8 2155.94    37.8 2150.86    43.9 2147.01
      51 2143.55    87.3 2130.29    95.9 2128.16   127.6 2122.87   132.9 2122.28
   152.3 2122.34   179.7 2121.08   203.6 2121.65  282.752121.177   294.4    2119
  309.082121.544   329.7 2122.09   371.7 2121.78   400.9 2123.03   407.7 2124.35
   431.4 2132.09   441.6 2134.25   495.9  2138.3   509.1 2138.15   533.2  2141.5
     540  2141.6   546.8 2143.95   560.3 2145.63   570.5 2149.05   580.7 2151.22
#Mann= 6 ,-1 , 0
       0      .1       0  110.95      .1       0  172.36      .1       0
  282.75    .045       0  309.08     .07       0  326.54      .1       0
#XS Ineff= 2 , 0
                          347.03         2131.93
Permanent Ineff=
       F       F
Bank Sta=282.75,309.08
XS Rating Curve= 0 ,0
Exp/Cntr=0.3,0.1

Type RM Length L Ch R = 1 ,7115    ,253.7,268.5,258.7
XS GIS Cut Line= 3
2111273.84800789331735.5002659562110922.45927495331865.361226693
2110717.59813613331945.222287446
#Sta/Elev= 30
       0 2168.96    16.6 2165.17    30.4 2163.27    37.4  2161.4    62.6 2151.04
    75.8 2144.84   103.8  2134.7   110.8 2132.85   117.8  2126.9   124.8 2124.98
   131.8 2122.09   149.4 2119.85   162.2 2119.69   166.8 2119.15   182.6    2120
  211.392119.746   219.2 2118.01     226 2119.23   231.4  2119.5   282.2 2119.59
   334.7 2121.03   369.6 2122.89   445.1 2124.54   463.1 2126.75   483.1 2130.85
   496.4 2132.74   517.5 2136.78   528.1 2139.28   535.1 2139.74   594.5 2156.74
#Mann= 5 ,-1 , 0
       0      .1       0  162.69     .05       0  211.39    .045       0
   231.4     .05       0  279.43      .1       0
#XS Ineff= 1 ,-1
  281.49  594.49 2127.19
Permanent Ineff=
       F
Bank Sta=211.39,231.4
XS Rating Curve= 0 ,0
Exp/Cntr=0.3,0.1

Type RM Length L Ch R = 1 ,6847    ,201.4,214.6,209.6
XS GIS Cut Line= 3
2111215.51479122331588.9723437882110906.48686597331648.694665283
2110633.04942071331696.437680036
#Sta/Elev= 30
       0 2164.82     9.7 2163.03    19.7 2160.52    33.1  2156.3    63.2 2147.86
    99.9 2135.02   123.3 2124.19   133.3  2120.5   143.3  2119.6   200.5 2119.38
  213.132118.601   226.9 2116.92  233.132118.493   250.3 2118.66     257 2119.52
   285.2 2119.24   297.1 2118.57   333.8 2118.84   368.6 2117.91   374.3 2118.77
   383.7 2121.38   416.8 2122.19   443.7 2125.13     457 2125.94     467 2127.49
   483.6    2131   526.9 2142.45   536.9  2143.2   546.4 2146.75   592.3 2157.96
#Mann= 3 ,-1 , 0
       0      .1       0  213.13    .045       0  233.13      .1       0
Bank Sta=213.13,233.13
XS Rating Curve= 0 ,0
Exp/Cntr=0.3,0.1

Type RM Length L Ch R = 1 ,6632    ,273.9,277.2,277.1
XS GIS Cut Line= 3
2111175.75765288331443.6599703582110815.34105086331522.132254362
2110611.17446446  331582.5488002
#Sta/Elev= 30
       0 2152.52    16.1 2153.13    31.9 2151.91    39.6 2150.92      53 2147.59
    69.8  2144.5   116.8 2126.91   139.4 2120.69   163.8 2119.42   180.6 2119.95
   210.8 2118.83   271.2 2118.54   281.3  2117.7     288 2118.63  303.582117.677
   311.5  2117.1   324.2 2114.93   328.3 2115.24   331.7 2117.17  336.222117.941
   341.7 2118.46   348.5 2118.05   355.2 2118.87   368.6 2123.49   375.4 2125.01
   416.5 2127.74   459.8 2131.88   534.6 2143.29   553.1 2144.99   581.8 2145.25
#Mann= 3 ,-1 , 0
       0      .1       0  303.58    .045       0  336.22      .1       0
Bank Sta=303.58,336.22
XS Rating Curve= 0 ,0
Exp/Cntr=0.3,0.1

Type RM Length L Ch R = 1 ,6355    ,251.5,258.5,265.9
XS GIS Cut Line= 2
2111141.73016188331285.3266256152110560.48001203 331256.85424161
#Sta/Elev= 30
       0 2146.26    24.3 2143.08    40.8 2142.12      67 2139.09    70.3 2138.33
    80.2 2134.45    93.3 2128.07   109.7 2123.07   122.9 2119.99     136 2119.53
   152.4 2116.81   172.2 2116.31   192.2 2117.85     205 2117.26   237.8 2117.67
   284.8  2116.5   339.7 2116.99  346.552116.342   356.1 2114.13  365.022116.055
   375.8 2115.96   395.7 2117.11   421.8 2115.69   425.1 2116.19   428.4 2117.76
   431.6 2121.18   438.2  2126.8   441.5  2128.4   444.8 2129.04   581.9 2144.02
#Mann= 6 ,-1 , 0
       0      .1       0  191.53     .05       0  228.78     .07       0
  346.55    .045       0  365.02     .07       0  400.25      .1       0
Bank Sta=346.55,365.02
XS Rating Curve= 0 ,0
Exp/Cntr=0.3,0.1

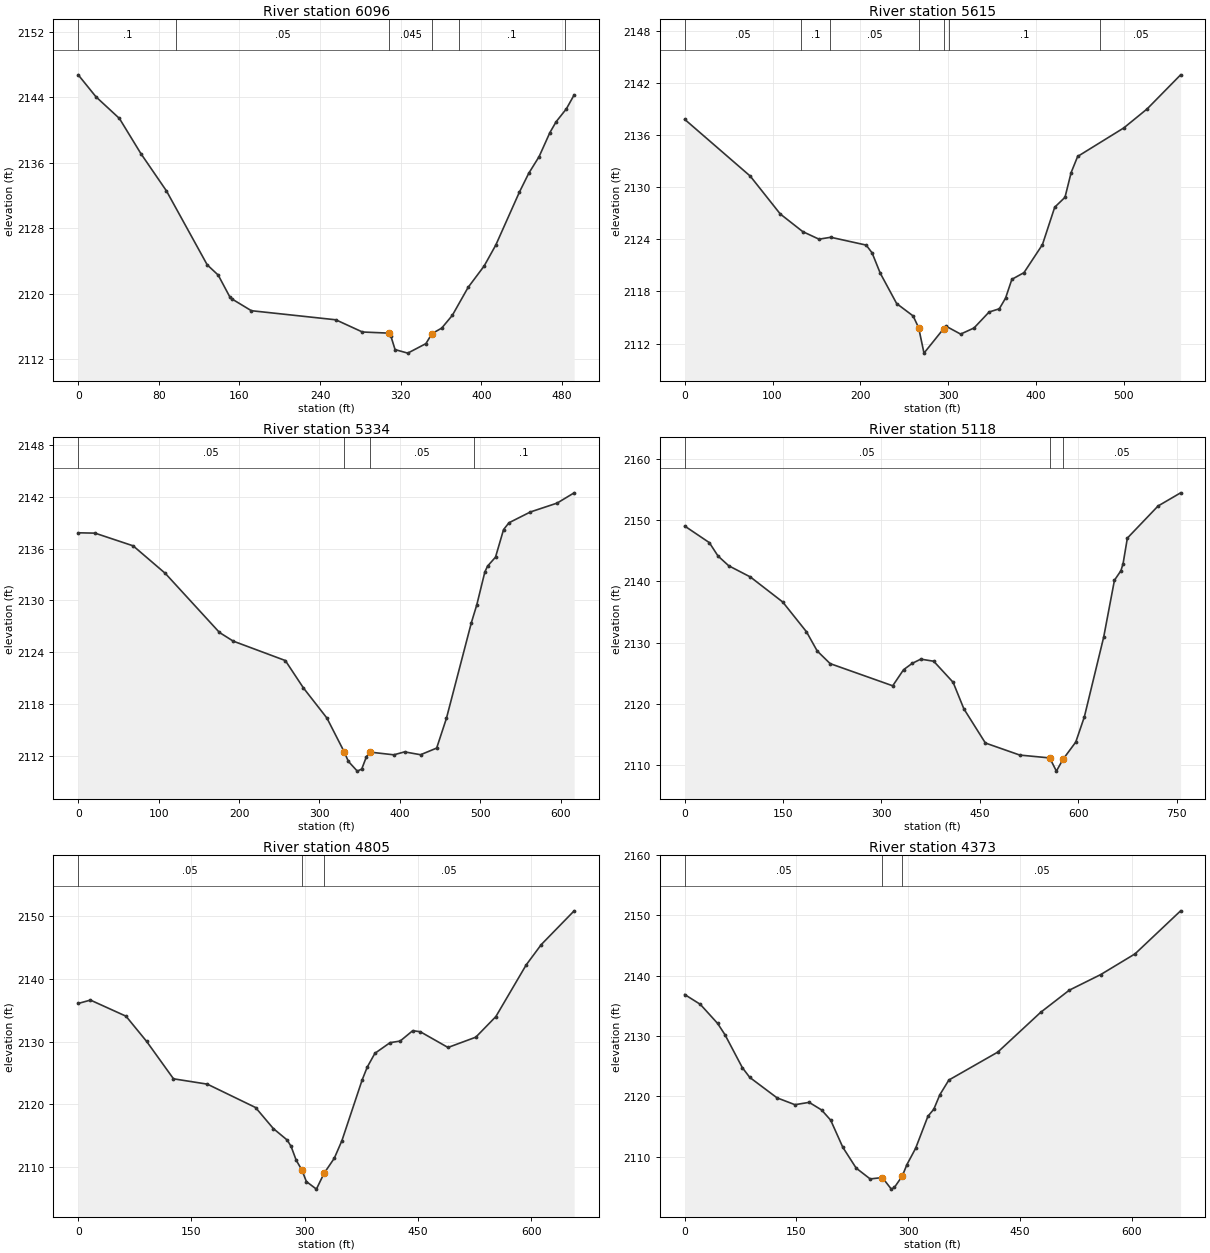
Type RM Length L Ch R = 1 ,6096    ,472.4,481.1,454.1
XS GIS Cut Line= 2
2111152.84103203331248.520924956 2110768.8132568330940.882104531
#Sta/Elev= 30
       0 2146.73    17.6 2144.05    40.9  2141.4    62.2 2137.11    87.6 2132.55
     128 2123.53   138.9 2122.28   150.5  2119.6     153 2119.33   171.8 2117.93
   255.6 2116.82     282 2115.33  308.362115.191   310.2 2114.85   314.4 2113.18
     327 2112.75     345 2113.91     3512115.125   360.7 2115.81   371.2 2117.36
   386.9 2120.78   402.8 2123.39   414.4 2125.96   437.7 2132.39     447  2134.7
   457.3 2136.74     468 2139.67   474.2    2141   484.4 2142.58   492.1 2144.28
#Mann= 6 ,-1 , 0
       0      .1       0   97.37     .05       0  308.36    .045       0
     351     .05       0  377.84      .1       0  483.32     .05       0
Bank Sta=308.36,351
XS Rating Curve= 0 ,0
Exp/Cntr=0.3,0.1

Type RM Length L Ch R = 1 ,5615    ,286,281.3,266.7
XS GIS Cut Line= 3
2111347.98007745  331083.93759272111193.81339103330913.798825368
2110929.92448312330707.548909783
#Sta/Elev= 30
       0  2137.8    74.6 2131.27   108.8 2126.91   134.4 2124.88   152.9 2124.01
   166.3 2124.23   206.6 2123.33   213.3 2122.44   222.6  2120.1   241.3  2116.6
     260 2115.18   266.32113.828   272.4  2110.9  294.632113.699   297.4    2114
   314.1 2113.09   329.3 2113.79   346.5 2115.63   358.1    2116   365.2 2117.22
   372.4 2119.39   386.2 2120.16   407.2 2123.38   421.2 2127.69   432.9 2128.83
   439.9 2131.68   447.3 2133.53   499.8 2136.81   526.4    2139   564.5 2142.92
#Mann= 7 ,-1 , 0
       0     .05       0  132.95      .1       0  165.82     .05       0
   266.3    .045       0  294.63     .05       0  300.74      .1       0
  472.78     .05       0
Bank Sta=266.3,294.63
XS Rating Curve= 0 ,0
Exp/Cntr=0.3,0.1

Type RM Length L Ch R = 1 ,5334    ,217.6,216.2,208
XS GIS Cut Line= 3
2111628.39651138 330835.048654782111377.35501871330714.215563118
2111044.02169588330656.923682943
#Sta/Elev= 30
       0 2137.84    20.9  2137.8    68.3 2136.33   108.3 2133.14   175.7 2126.29
   192.8 2125.29   257.6 2123.04     280 2119.88   309.3 2116.38  330.642112.495
     336 2111.36   347.1 2110.23   352.6 2110.47   358.5 2111.91  363.162112.431
   392.5 2112.12   405.9 2112.46   425.8 2112.13   445.8  2112.9   457.9 2116.33
     489 2127.44   495.7 2129.49   505.7 2133.29   509.1 2133.98     519 2135.02
     529 2138.21   535.7    2139   562.3 2140.25   595.6 2141.28   616.8 2142.47
#Mann= 4 ,-1 , 0
       0     .05       0  330.64    .045       0  363.16     .05       0
  492.35      .1       0
Bank Sta=330.64,363.16
XS Rating Curve= 0 ,0
Exp/Cntr=0.3,0.1

Type RM Length L Ch R = 1 ,5118    ,312.5,313.1,302.1
XS GIS Cut Line= 3
2111824.23010921330475.6737173652111441.93822289330503.798661113
2111069.02164587330503.798661113
#Sta/Elev= 30
       0 2149.02    37.6 2146.31    50.8 2144.13    67.2 2142.53   100.1 2140.71
   149.5 2136.62   185.7 2131.76   202.1 2128.62   221.8 2126.56   317.2 2122.94
   333.7 2125.56   346.9  2126.6     360 2127.29   379.7 2126.95   409.3 2123.51
   425.7 2119.18   458.5  2113.6     511 2111.63  556.592111.165   566.8 2109.01
  576.832110.933   596.3 2113.75   609.4 2117.86   638.9 2130.89   655.3 2140.17
   665.2 2141.73   668.5  2142.9     675 2147.05   721.8 2152.29   756.2 2154.44
#Mann= 3 ,-1 , 0
       0     .05       0  556.59    .045       0  576.83     .05       0
Bank Sta=556.59,576.83
XS Rating Curve= 0 ,0
Exp/Cntr=0.3,0.1

Type RM Length L Ch R = 1 ,4805    ,415.3,431.5,438.4
XS GIS Cut Line= 3
2111645.06347278330215.2572434542111254.43826979330303.798733026
2111002.35511255330350.673639283
#Sta/Elev= 30
       0  2136.1    16.2 2136.64    63.3 2134.07    90.6 2130.05   126.2 2124.08
     171 2123.23   234.9  2119.5   258.4 2116.15   276.8 2114.31     282 2113.29
   288.7  2111.1  296.332109.519   302.2 2107.69   315.5 2106.48  325.64    2109
   339.2 2111.41   349.3 2114.22   376.2 2123.94   382.9 2125.96     393 2128.15
   413.1 2129.85   426.4  2130.1   443.1 2131.76   453.1 2131.59   489.8 2129.08
   526.6 2130.72   553.2 2134.01   593.3 2142.24   613.3 2145.49   656.9 2150.88
#Mann= 3 ,-1 , 0
       0     .05       0  296.33    .045       0  325.64     .05       0
Bank Sta=296.33,325.64
XS Rating Curve= 0 ,0
Exp/Cntr=0.3,0.1

Type RM Length L Ch R = 1 ,4373    ,181.6,188.1,196.2
XS GIS Cut Line= 4
2111528.39671138330000.6736831222111363.81337914329972.548739359
2111210.68835729329860.0486362872110947.14656153329699.631962359
#Sta/Elev= 30
       0 2136.89    20.9 2135.27    44.2  2132.1    54.1 2130.22    77.4 2124.76
    87.4 2123.14   123.9 2119.76     148 2118.62     167 2119.01   183.7 2117.75
   195.9 2116.06   212.2 2111.56   230.1 2108.11   248.9 2106.31  265.252106.538
   277.3 2104.62   281.4  2104.9  291.91 2106.77   298.2 2108.68   309.9 2111.39
   326.4  2116.7   334.3 2117.87   342.4 2120.27   354.5 2122.71   420.1 2127.34
   477.7 2133.94   516.1 2137.61   558.3  2140.2   604.4 2143.64   665.5 2150.77
#Mann= 3 ,-1 , 0
       0     .05       0  265.25    .045       0  291.91     .05       0
Bank Sta=265.25,291.91
XS Rating Curve= 0 ,0
Exp/Cntr=0.5,0.3

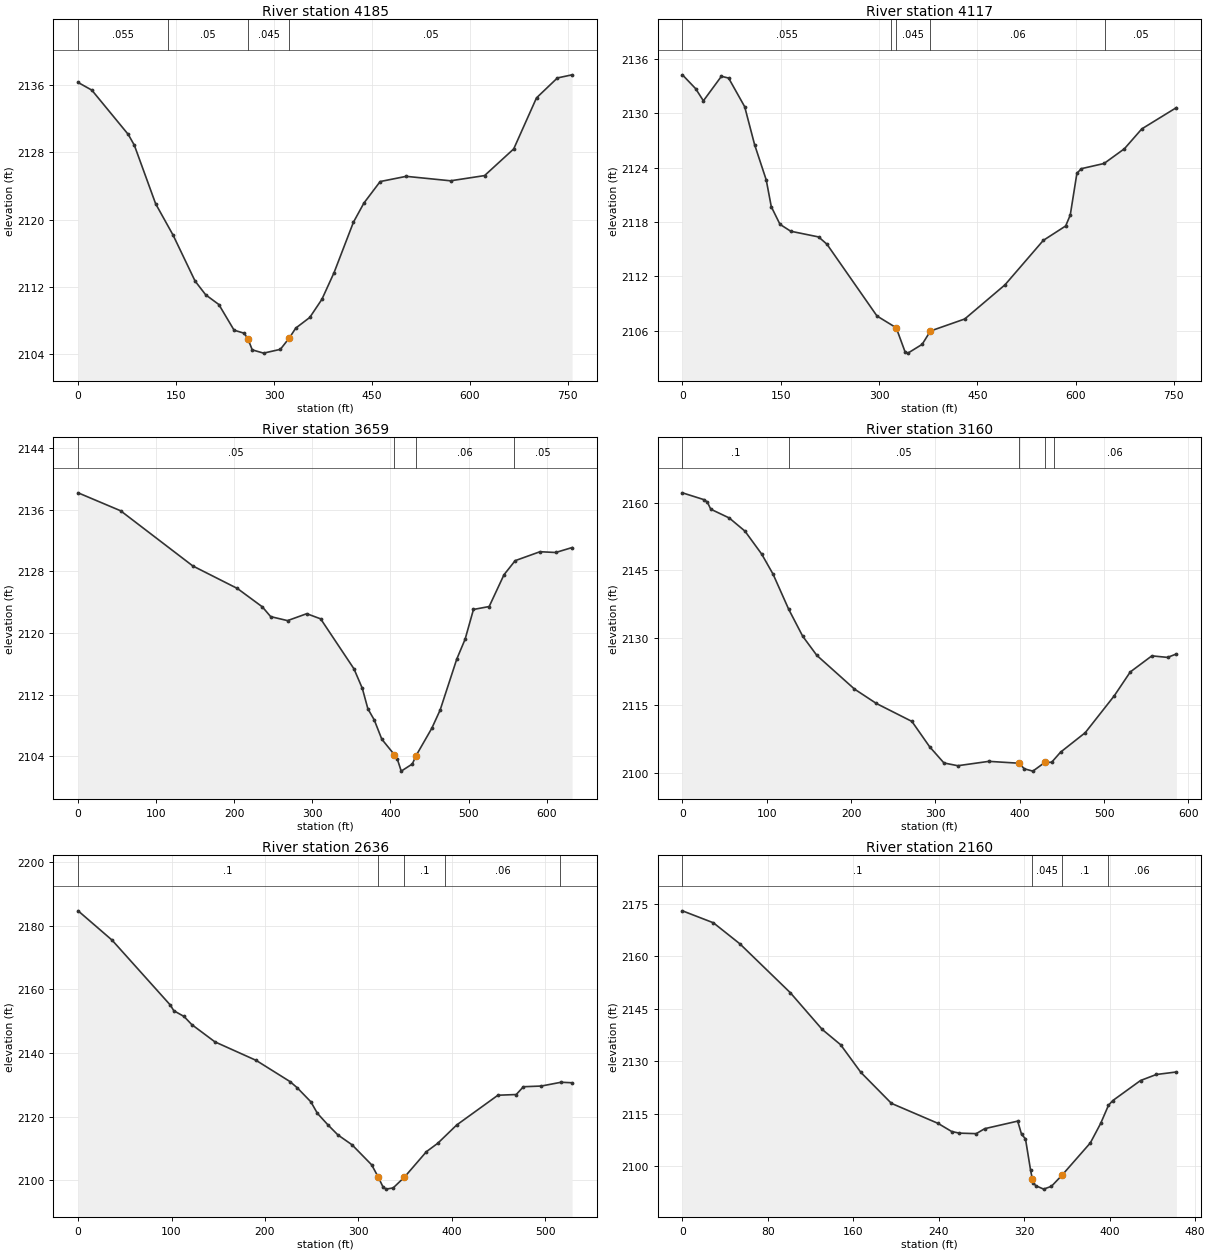
Type RM Length L Ch R = 1 ,4185    ,75.8,68.3,70.4
XS GIS Cut Line= 4
 2111534.4255707329953.2170851082111372.09912372329766.585240528
2111309.59924871329717.9741172792110930.25880003329515.717303947
#Sta/Elev= 30
       0 2136.32      21 2135.41    76.8 2130.14    86.1 2128.86   118.7  2121.9
   145.5 2118.16   179.1 2112.71   195.4 2111.07   215.5 2109.92   238.8 2106.87
   254.1 2106.51  260.022105.843   266.6 2104.53     284 2104.14   309.7 2104.59
  323.36 2105.94   333.3 2107.12   354.7 2108.38   373.3 2110.54   391.9 2113.71
   421.6 2119.71   437.6 2121.98   462.5 2124.54   502.4 2125.16   570.3 2124.63
   622.4 2125.25     667 2128.42   701.9 2134.49   733.9 2136.86   756.4 2137.23
#Mann= 4 ,-1 , 0
       0    .055       0   137.7     .05       0  260.02    .045       0
  323.36     .05       0
#XS Ineff= 2 , 0
          230.02  2107.6  353.36          2107.6
Permanent Ineff=
       F       F
Bank Sta=260.02,323.36
XS Rating Curve= 0 ,0
Exp/Cntr=0.5,0.3

Type RM Length L Ch R = 1 ,4117    ,465.4,458.1,401.2
XS GIS Cut Line= 6
2111589.11312538329906.993096203 2111532.6893537329830.604469448
2111356.43937811329685.9167667032111321.85611397329655.916826695
2111171.27275372 329528.416753622110992.83544654329470.187539369
#Sta/Elev= 30
       0 2134.25    20.2 2132.72      32 2131.38    59.5 2134.09    70.5 2133.89
      95 2130.73   110.1 2126.55   127.9 2122.64   135.6 2119.69   148.9 2117.74
   165.3 2116.98   207.8 2116.35   220.5 2115.55   296.9 2107.62  326.27 2106.32
   339.7 2103.67   344.1 2103.52   365.8 2104.49  378.492105.964   430.8 2107.29
   492.2 2111.06   550.7 2115.97   584.8 2117.56   591.8 2118.76     602 2123.39
   608.9 2123.89   643.4 2124.46   674.5 2126.09     701 2128.28   753.8 2130.63
#Mann= 5 ,-1 , 0
       0    .055       0  317.79     .06       0  326.27    .045       0
  378.49     .06       0  645.11     .05       0
Bank Sta=326.27,378.49
XS Rating Curve= 0 ,0
Exp/Cntr=0.5,0.3

Type RM Length L Ch R = 1 ,3659    ,486.3,498.3,486.8
XS GIS Cut Line= 2
2111548.18833846329196.5069843682110964.85485947 329441.29881762
#Sta/Elev= 30
       0 2138.21    54.4 2135.88   146.9 2128.71   203.9 2125.79   235.9  2123.4
   246.6 2122.13   268.2 2121.61   292.8 2122.51   310.6 2121.84   353.3 2115.34
     364  2112.8   371.1 2110.15   379.2 2108.72   388.9 2106.21  405.042104.192
   408.6 2103.68   413.8 2102.06     428 2102.99  432.672104.052   452.9 2107.62
   463.6 2109.99   484.9 2116.61   495.6  2119.2   506.3 2123.06   526.4 2123.44
   545.4 2127.57   559.7  2129.4   591.5 2130.56   611.6 2130.46   632.6  2131.1
#Mann= 4 ,-1 , 0
       0     .05       0  405.04    .045       0  432.67     .06       0
  558.11     .05       0
Bank Sta=405.04,432.67
XS Rating Curve= 0 ,0
Exp/Cntr=0.3,0.1

Type RM Length L Ch R = 1 ,3160    ,522.7,524.3,523.3
XS GIS Cut Line= 2
2111350.20218587328799.285009786 2110832.4939037329073.243123278
#Sta/Elev= 30
       0 2162.18    25.8 2160.65    29.5 2160.13    33.6 2158.55    55.5  2156.6
    74.1 2153.69      94 2148.58   107.5 2144.12     126 2136.34   142.6 2130.36
   159.4  2126.1     204 2118.63     230 2115.43   272.1 2111.45   293.1 2105.83
   310.1 2102.23   326.5 2101.62   363.3 2102.59  399.212102.173   405.4 2100.93
   415.5 2100.42  429.62 2102.34   437.8 2102.39   448.4 2104.64   477.6 2108.95
   512.1 2117.16     531 2122.43   556.6    2126   575.2 2125.66   585.7 2126.42
#Mann= 5 ,-1 , 0
       0      .1       0   126.1     .05       0  399.21    .045       0
  429.62     .05       0  440.63     .06       0
Bank Sta=399.21,429.62
XS Rating Curve= 0 ,0
Exp/Cntr=0.3,0.1

Type RM Length L Ch R = 1 ,2636    ,475.1,476.5,472.8
XS GIS Cut Line= 2
2110979.36893803328428.4514338672110506.45223296 328664.90995045
#Sta/Elev= 30
       0 2184.73    36.4  2175.5    98.7  2155.1   102.4 2153.33   113.4 2151.51
   121.6 2148.98   146.4 2143.54   190.5 2137.72   226.8 2131.05   234.5 2129.11
   249.1 2124.69   256.1 2121.07   267.5  2117.4   278.1 2114.27   293.2 2111.17
   314.2 2104.87   320.9  2101.2   326.2 2098.01   329.5 2097.24   337.2 2097.62
  349.23    2101   372.8 2109.02   384.9 2111.65   405.3 2117.43   449.3 2126.76
   468.9 2126.98   476.6 2129.43   495.8 2129.65   516.9 2130.84   528.7 2130.68
#Mann= 5 ,-1 , 0
       0      .1       0   320.9    .045       0  349.23      .1       0
  393.11     .06       0  516.02     .05       0
Bank Sta=320.9,349.23
XS Rating Curve= 0 ,0
Exp/Cntr=0.3,0.1

Type RM Length L Ch R = 1 ,2160    ,309,308.2,304.2
XS GIS Cut Line= 3
2110734.57710481328009.7016151992110486.66060588328178.451605782
2110342.91056529328254.493120372
#Sta/Elev= 30
       0 2173.04      29 2169.62    53.8 2163.61     101 2149.65   130.9 2139.15
   148.1 2134.79   167.1 2126.87   195.7 2118.03   239.3 2112.32   252.1 2109.99
   259.2 2109.53   275.1 2109.38     283  2110.8   313.9 2112.96   317.5 2109.21
   321.2 2107.88     326 2098.88  327.612096.442   328.6 2095.26   330.9  2094.5
   338.2 2093.53   345.5 2094.34  355.192097.436   381.9 2106.73   391.6 2112.31
   398.9 2117.48   402.9 2118.82   428.9 2124.56   443.7 2126.28   462.5    2127
#Mann= 4 ,-1 , 0
       0      .1       0  327.61    .045       0  355.19      .1       0
  398.55     .06       0
Bank Sta=327.61,355.19
XS Rating Curve= 0 ,0
Exp/Cntr=0.3,0.1

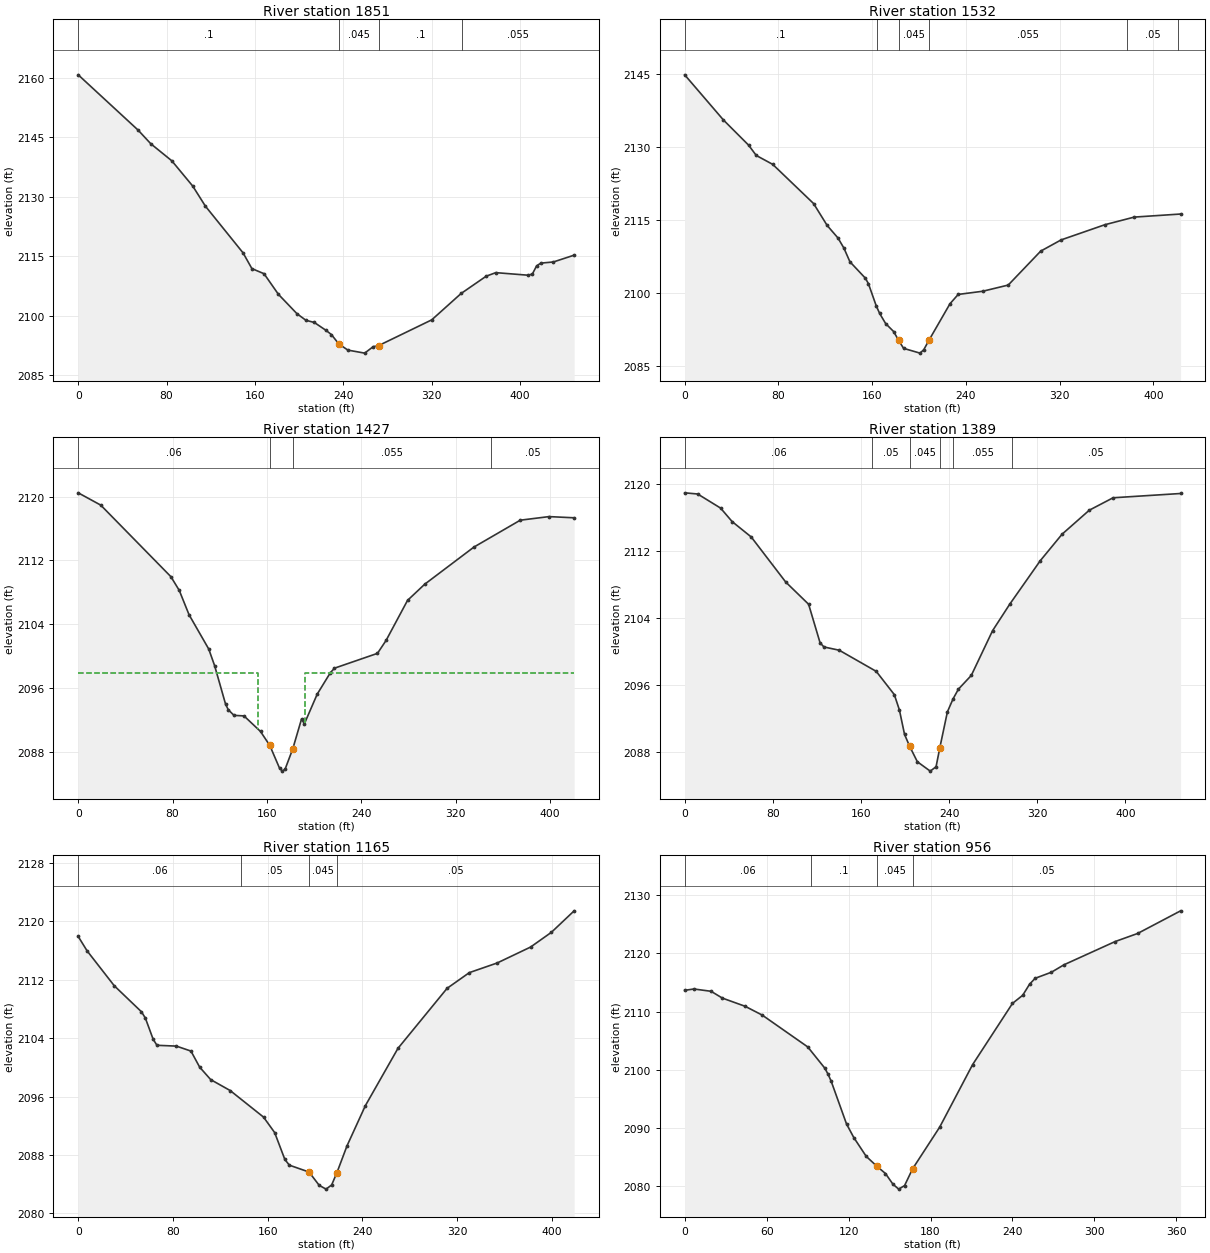
Type RM Length L Ch R = 1 ,1851    ,324.8,319.1,313.8
XS GIS Cut Line= 2
2110577.11186853327797.2594547872110189.09099105328022.953885287
#Sta/Elev= 30
       0 2160.68    54.3 2146.72    65.7  2143.3    84.7 2139.01   103.7 2132.62
   115.1 2127.58   149.2  2115.8   157.2 2111.83   168.2 2110.54   181.2 2105.35
     198 2100.46   206.1  2098.8   213.7 2098.25   224.4 2096.24   229.2 2095.19
  235.91 2092.83   244.1 2091.28   259.3 2090.52   266.9 2092.13  271.952092.425
     320 2098.91   346.6 2105.56   369.3 2109.92     378 2110.81   407.3 2110.16
   411.1 2110.47   414.9 2112.51   418.7 2113.21   430.1  2113.5   448.9 2115.22
#Mann= 4 ,-1 , 0
       0      .1       0  235.91    .045       0  271.95      .1       0
  347.43    .055       0
Bank Sta=235.91,271.95
XS Rating Curve= 0 ,0
Exp/Cntr=0.3,0.1

Type RM Length L Ch R = 1 ,1532    ,124.2,104.9,91
XS GIS Cut Line= 3
2110273.29259428327540.3150867822110109.26470712327734.724802956
2110163.91748497327894.481701285
#Sta/Elev= 30
       0 2144.75    33.1 2135.48    54.5 2130.34    61.1 2128.21    75.1 2126.39
     110 2118.35   121.6 2113.85   130.8 2111.29   135.9  2109.2     141 2106.41
   154.2 2103.04   156.8 2101.91   163.5 2097.34   166.4  2095.8   171.5 2093.73
   178.3  2092.1  182.622090.264   186.8 2088.65   200.8 2087.67     204 2088.36
  208.712090.422   226.4  2097.8   233.4 2099.71   254.3 2100.36   276.1 2101.63
   303.8 2108.59   321.2 2110.89   358.6 2114.01   383.6 2115.57   423.2  2116.2
#Mann= 6 ,-1 , 0
       0      .1       0  164.05    .055       0  182.62    .045       0
  208.71    .055       0  377.64     .05       0  421.31     .06       0
Bank Sta=182.62,208.71
XS Rating Curve= 0 ,0
Exp/Cntr=0.5,0.3

Type RM Length L Ch R = 1 ,1427    ,39.2,38.8,39
XS GIS Cut Line= 5
2109981.30761397327528.8682592812110036.30750397327657.201664031
2110080.75196889327695.5349206922110124.64098871 327786.09051387
2110155.19637379327903.868165448
#Sta/Elev= 30
       0 2120.48    19.1 2118.94    78.6 2109.97    85.7 2108.25      94  2105.2
   110.7  2100.9   115.7 2098.81     125 2093.98   127.3 2093.29   132.1 2092.59
   140.6 2092.52   154.6 2090.57  162.452088.825   170.8 2085.95   173.2  2085.6
   175.5 2085.86  182.012088.416   189.4 2092.13   191.8 2091.53   202.7 2095.25
   213.7  2097.9   217.3  2098.5   253.8 2100.36   261.1 2101.98   279.3    2107
   293.9 2109.03   335.6 2113.68   374.9 2117.05   399.3  2117.5   420.6 2117.35
#Mann= 4 ,-1 , 0
       0     .06       0  162.45    .045       0  182.01    .055       0
  349.72     .05       0
#XS Ineff= 2 , 0
          152.45  2097.9  192.01          2097.9
Permanent Ineff=
       F       F
Bank Sta=162.45,182.01
XS Rating Curve= 0 ,0
Exp/Cntr=0.5,0.3

Type RM Length L Ch R = 1 ,1389    ,197.5,223.2,240.7
XS GIS Cut Line= 5
2109945.75191081327517.7570610342110001.86301905327679.979505613
2110077.41864222327742.2014940382110132.97430536327875.534888789
 2110139.6409587327911.090591952
#Sta/Elev= 30
       0 2118.91    11.8 2118.77    32.6 2117.09    43.1 2115.48    60.4 2113.65
    91.7 2108.28   112.5 2105.63   122.9 2101.04   126.4 2100.54   140.3 2100.15
   173.9 2097.63   190.3 2094.86   194.9 2093.04   199.6 2090.11  204.282088.683
   211.2 2086.86   222.9 2085.74   228.2 2086.26  231.632088.538   238.5 2092.81
   243.7 2094.37   248.5 2095.51   260.2 2097.15   279.5 2102.48   295.1 2105.64
   322.8 2110.82   342.6 2113.98   367.3 2116.84   388.9 2118.32   450.2 2118.83
#Mann= 6 ,-1 , 0
       0     .06       0     170     .05       0  204.28    .045       0
  231.63     .05       0   243.7    .055       0  297.02     .05       0
Bank Sta=204.28,231.63
XS Rating Curve= 0 ,0
Exp/Cntr=0.5,0.3

Type RM Length L Ch R = 1 ,1165    ,207.9,209.4,210.8
XS GIS Cut Line= 3
2109940.93138239327524.7245667872109942.04260063327621.391368195
2109717.04239446327851.947009444
#Sta/Elev= 30
       0 2117.92     7.5 2115.95    30.4 2111.18    53.4 2107.61    56.7 2106.75
    63.3 2103.84    66.5 2103.02    82.9 2102.91    95.2 2102.23   102.6 2100.02
   111.9 2098.32   128.3 2096.83   156.5 2093.19   165.9 2091.07   174.5 2087.39
   178.3 2086.61  194.932085.669   203.5 2083.85   209.3 2083.33     214  2083.9
  218.452085.577     227 2089.26   242.5 2094.76     270  2102.6   311.5 2110.82
   330.3 2112.97   353.8 2114.29     382 2116.47   399.6 2118.49   418.8 2121.43
#Mann= 4 ,-1 , 0
       0     .06       0  137.67     .05       0  194.93    .045       0
  218.45     .05       0
Bank Sta=194.93,218.45
XS Rating Curve= 0 ,0
Exp/Cntr=0.3,0.1

Type RM Length L Ch R = 1 ,956     ,247.1,247.8,246.4
XS GIS Cut Line= 2
 2109869.4961578 327436.252630862109583.38518146327659.863732204
#Sta/Elev= 30
       0 2113.65     6.8 2113.87    19.3 2113.48    27.6 2112.31    44.3  2110.9
    56.8 2109.39    90.1 2103.93   102.6 2100.28   104.9 2099.28   107.2 2098.08
   118.5  2090.7   123.8 2088.38   132.9 2085.15  140.672083.454     147  2082.2
   152.5 2080.36   156.7 2079.52     161 2080.13  166.87 2083.01   186.7 2090.16
   210.8 2100.89     240  2111.4   247.5  2112.8   252.5 2114.69   256.6 2115.71
   268.5 2116.75   277.8 2118.04   315.2 2122.02   331.6  2123.4   363.1 2127.29
#Mann= 4 ,-1 , 0
       0     .06       0   92.52      .1       0  140.67    .045       0
  166.87     .05       0
Bank Sta=140.67,166.87
XS Rating Curve= 0 ,0
Exp/Cntr=0.3,0.1