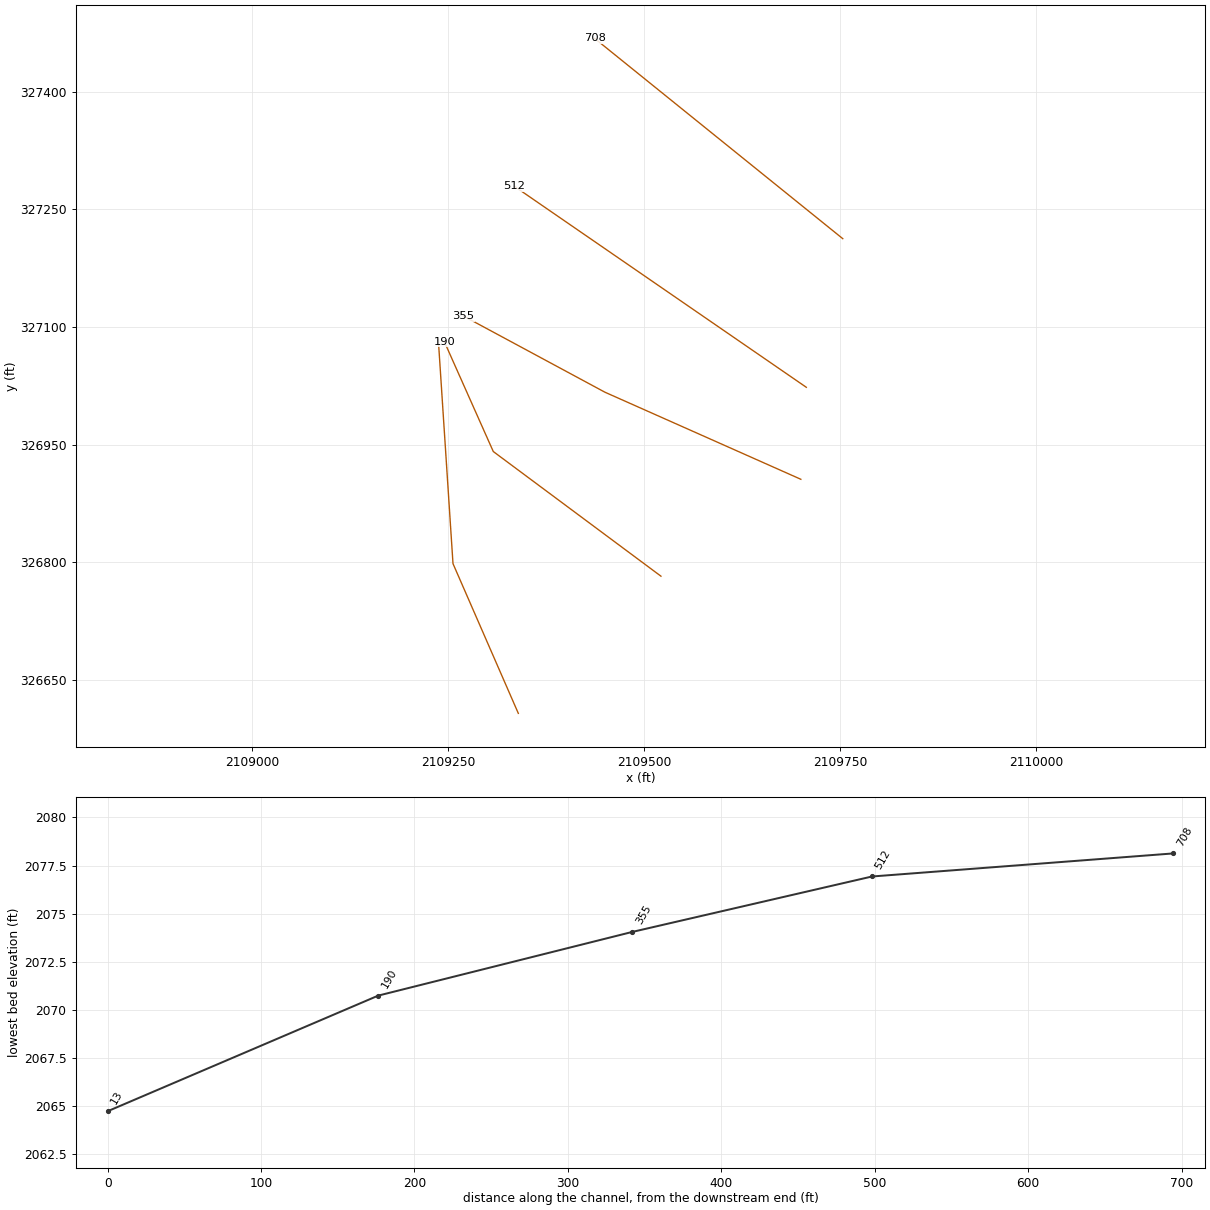
HEC-RAS study MLGNCKTR5.prj: MLGNCKTR5

--- MLGNCKTR5.g01 (geometry) --- (continued)

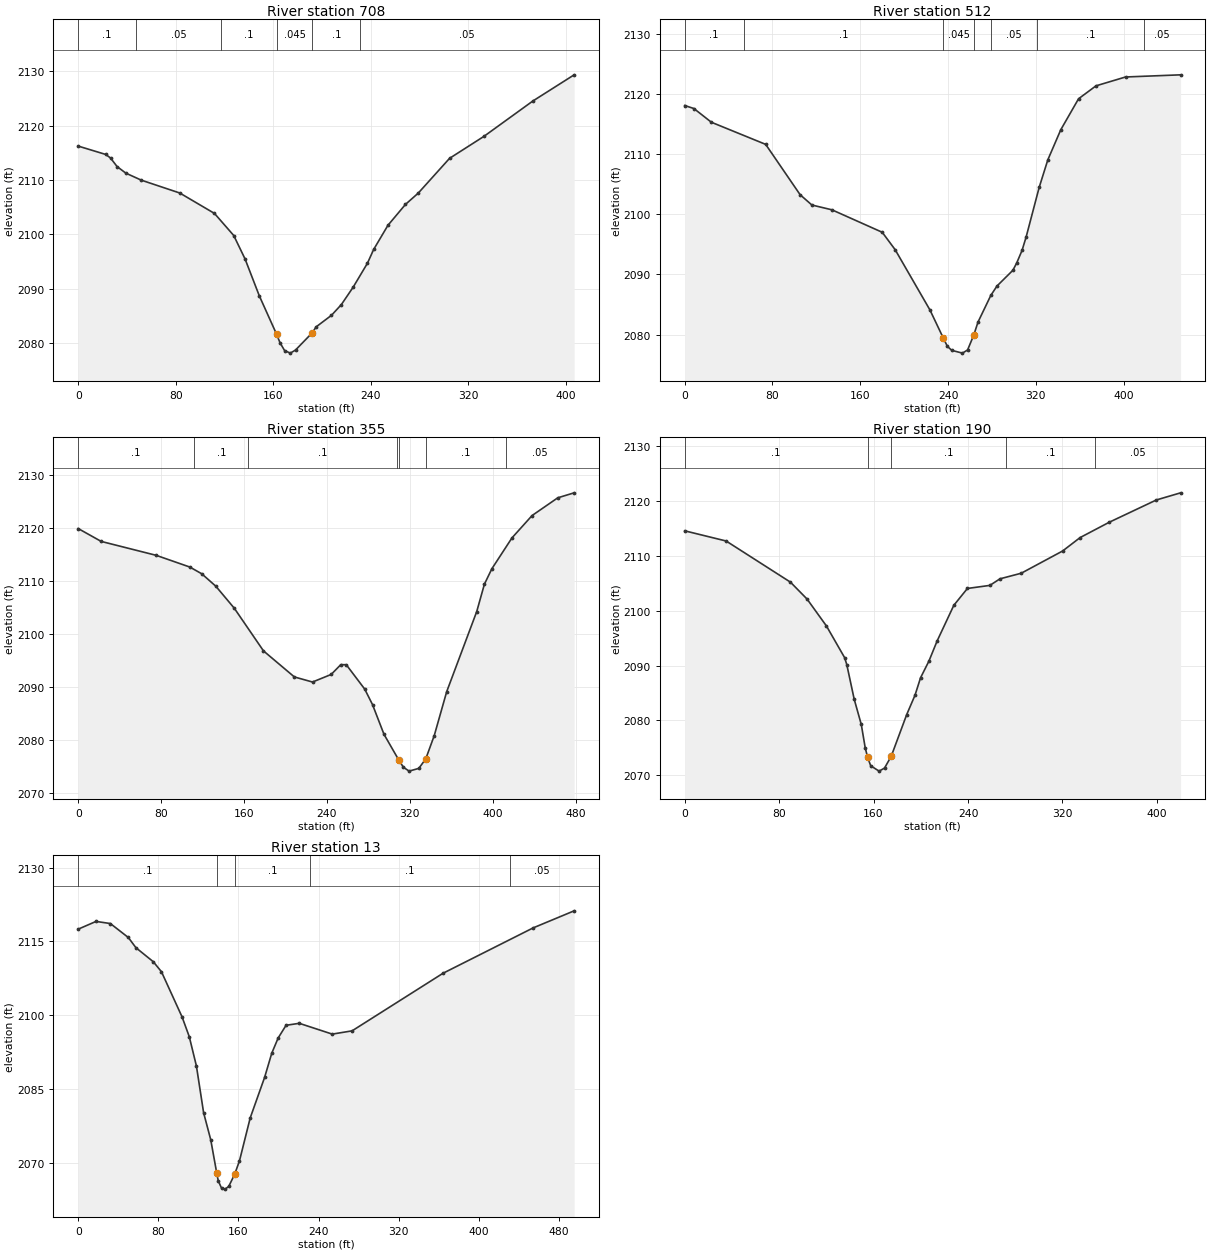
Type RM Length L Ch R = 1 ,708     ,195.3,196.5,197.5
XS GIS Cut Line= 2
2109753.52394879 327212.64152953 2109436.8572593327468.196792692
#Sta/Elev= 30
       0 2116.22    22.6 2114.68    26.5 2114.03    31.9 2112.45    39.1 2111.24
    51.8 2109.95    83.3 2107.59   111.8 2103.83   127.6 2099.77   136.9 2095.45
   148.6 2088.66  162.772081.597   165.6 2080.03   169.3 2078.61     174 2078.13
   178.3  2078.7  192.072081.884   195.2 2082.96   207.8 2085.09   215.9 2087.06
   225.6 2090.27   237.3 2094.67   242.4  2097.2   254.1 2101.64   268.5 2105.49
     279 2107.57   304.7 2113.97   332.9 2118.01     373 2124.51   406.9 2129.33
#Mann= 6 ,-1 , 0
       0      .1       0   47.61     .05       0  117.12      .1       0
  162.77    .045       0  192.07      .1       0  231.46     .05       0
Bank Sta=162.77,192.07
XS Rating Curve= 0 ,0
Exp/Cntr=0.3,0.1

Type RM Length L Ch R = 1 ,512     ,155.7,156.2,158.2
XS GIS Cut Line= 2
 2109706.9961547327023.0579192042109334.77413014327279.308062866
#Sta/Elev= 30
       0 2118.09     8.4 2117.59    24.3 2115.31    73.8 2111.63   105.2 2103.26
   115.9 2101.55   134.2 2100.75     180 2097.02   191.8 2094.12   223.5  2084.1
  235.772079.388   239.4 2078.05   243.4 2077.39   253.1 2076.93   257.8 2077.46
  263.442079.948   267.3  2082.1     279 2086.54   284.6 2088.09   299.1 2090.71
   302.6 2091.94   307.4    2094   311.1 2096.21     323 2104.47   330.9 2109.06
   342.7 2114.06   358.9 2119.21   374.8 2121.36   401.7 2122.83   451.9 2123.19
#Mann= 7 ,-1 , 0
       0      .1       0   53.75      .1       0  235.77    .045       0
  263.44      .1       0  278.73     .05       0  320.93      .1       0
  418.48     .05       0
Bank Sta=235.77,263.44
XS Rating Curve= 0 ,0
Exp/Cntr=0.3,0.1

Type RM Length L Ch R = 1 ,355     ,167.5,165.6,166.6
XS GIS Cut Line= 3
2109700.05161479326905.6969334482109450.05178672327016.807931691
2109269.49604547327114.030178204
#Sta/Elev= 30
       0 2119.87    22.2 2117.44    75.3 2114.81   107.7  2112.6   119.2 2111.33
   132.8 2108.98   150.7  2104.8   178.8 2096.76   208.6 2091.84   226.1 2090.88
   244.1 2092.31   253.4 2094.16   258.7 2094.15   276.5 2089.54     284 2086.62
   295.1    2081  309.38 2076.14   313.8 2074.79   319.3 2074.05   328.7 2074.57
  335.422076.375   343.6 2080.77   355.6 2089.06   384.6  2104.2     392 2109.37
   399.2 2112.28   418.6 2118.11     438 2122.33   462.8 2125.68   478.6 2126.62
#Mann= 7 ,-1 , 0
       0      .1       0   111.8      .1       0  164.31      .1       0
  307.67      .1       0  309.38    .045       0  335.42      .1       0
  412.78     .05       0
Bank Sta=309.38,335.42
XS Rating Curve= 0 ,0
Exp/Cntr=0.3,0.1

Type RM Length L Ch R = 1 ,190     ,182.7,176.4,173.6
XS GIS Cut Line= 3
2109521.57953081326782.0859601942109307.69052288 326941.11352928
2109245.19064787 327081.39146395
#Sta/Elev= 30
       0 2114.59    35.1 2112.73    89.6 2105.22   103.7 2102.13   120.1 2097.22
   135.5 2091.44   137.3 2090.19   143.6 2083.86   149.6 2079.25   152.9 2075.03
   154.92073.298   157.6 2071.71   164.7 2070.74   169.3  2071.3  174.972073.455
   188.1 2081.07   195.1 2084.59   199.8 2087.77   206.9 2090.82   213.9 2094.52
     228    2101   239.5 2104.07   258.5 2104.63   267.1 2105.83   285.1 2106.85
   320.1  2110.9     335 2113.36   359.8 2116.17   399.6 2120.22   420.1 2121.52
#Mann= 5 ,-1 , 0
       0      .1       0   154.9    .045       0  174.97      .1       0
  272.28      .1       0  347.79     .05       0
Bank Sta=154.9,174.97
XS Rating Curve= 0 ,0
Exp/Cntr=0.3,0.1

Type RM Length L Ch R = 1 ,13      ,11.71,13.32,14.93
XS GIS Cut Line= 3
2109339.63501281326607.0859821142109256.30184612326798.058041111
2109237.55188364327084.169017449
#Sta/Elev= 30
       0 2117.49    17.8 2119.06    32.1 2118.63      50  2115.8    57.6 2113.73
      75 2110.87    83.1 2108.85   103.7 2099.67   110.9 2095.65     118 2089.72
   125.2 2080.22   132.3 2074.75  138.372067.909   139.8 2066.42   143.1 2064.92
   146.7 2064.73   150.3 2065.29  156.272067.785     161 2070.48   171.7 2079.18
   186.1 2087.42   193.2  2092.3   199.6  2095.4   207.5 2097.98   220.7 2098.38
   253.6 2096.19   273.4 2096.85   364.2 2108.54   454.2 2117.75   495.1 2121.21
#Mann= 5 ,-1 , 0
       0      .1       0  138.37    .045       0  156.27      .1       0
   231.4      .1       0  431.25     .05       0
Bank Sta=138.37,156.27
XS Rating Curve= 0 ,0
Exp/Cntr=0.3,0.1
LCMann Table=0

Chan Stop Cuts=-1
Use User Specified Reach Order=0
Composite Channel Slope=5